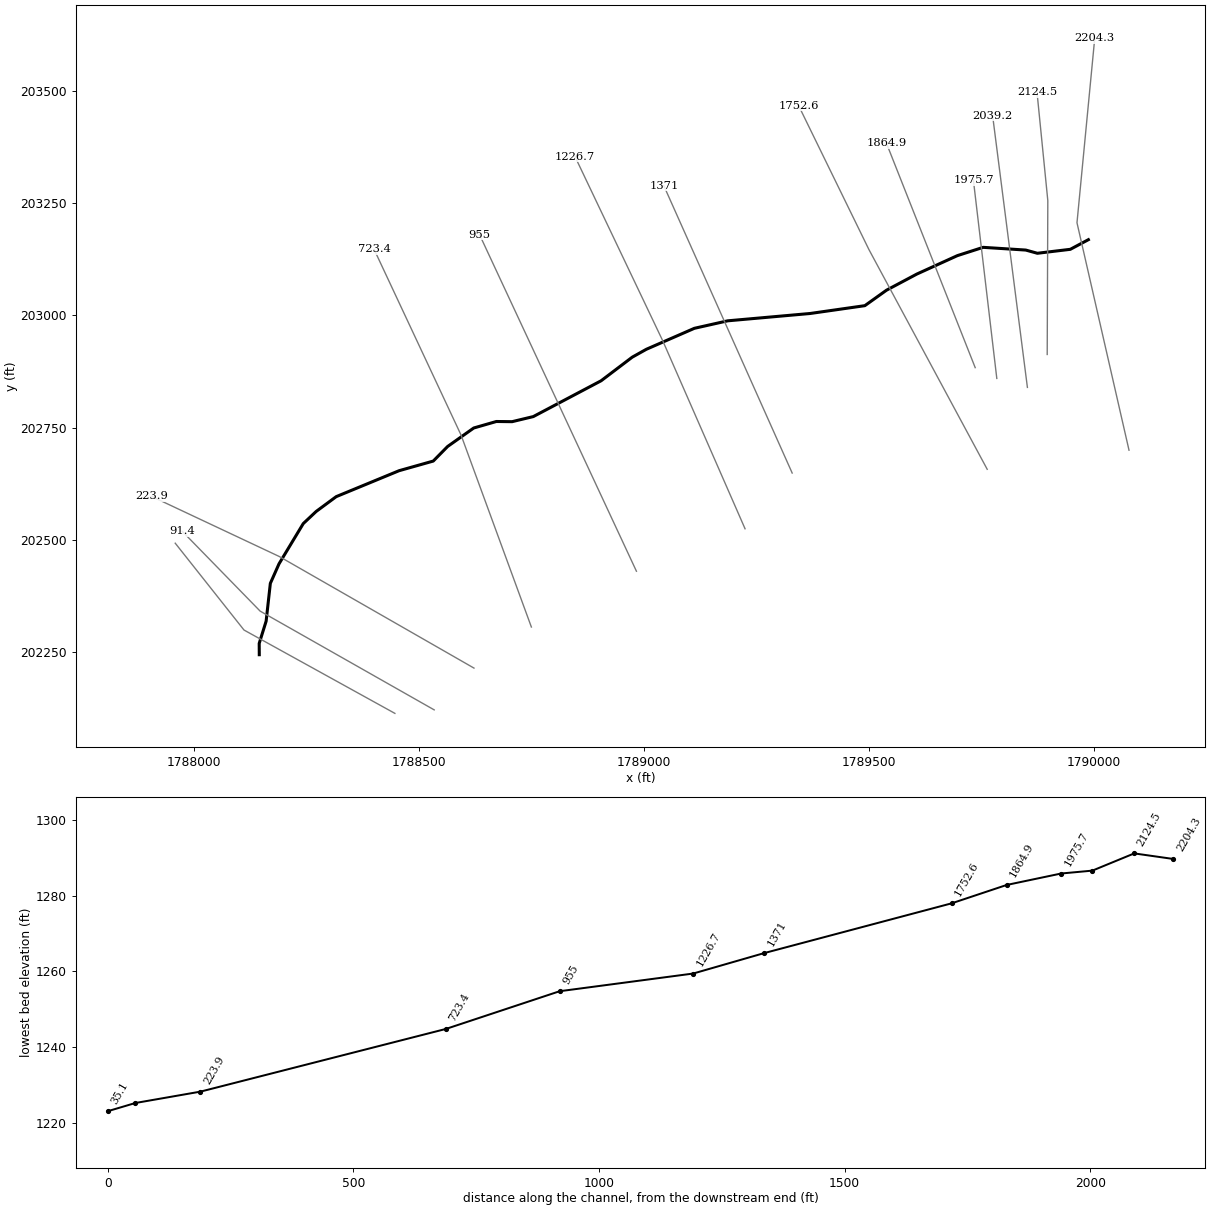
--- MileBr.prj (project) ---

Proj Title=MileBr
Current Plan=p01
Default Exp/Contr=0,0
English Units
Geom File=g01
Flow File=f01
Plan File=p01
BEGIN DESCRIPTION:
END DESCRIPTION:
DSS Export Rating Curves= 0
DSS Export Rating Curve Sorted= 0
DSS Export Volume Flow Curves= 0
DXF OffsetX= 0
DXF OffsetY= 0
DXF ScaleX= 0
DXF ScaleY= 0

--- MileBr.p01 (plan) ---

Plan Title=Floodplain
Program Version=4.00
Geom File=g01
Flow File=f01
K Sum by GR=0
Std Step Tol=0.01
Critical Tol=0.01
Num of Std Step Trials=20
Max Error Tol=0.3
Flow Tol Ratio=0.001
Split Flow NTrial=30
Split Flow Tol=0.02
Split Flow Ratio=0.02
Log Output Level=0
Friction Slope Method=1
Unsteady Friction Slope Method=2
Unsteady Bridges Friction Slope Method=1
Global Log Level=0
CheckData=False
Run HTab=0
Run UNet=0
Run PostProcess=0
UNET Theta=0
UNET Theta Warmup=0
UNET ZTol=0
UNET ZSATol=0
UNET MxIter=0
UNET MaxInSteps=0
UNET DtIC=0
UNET DtMin=0
UNET MaxCRTS=0
UNET WFStab=0
UNET SFStab=0
UNET WFX=0
UNET SFX=0
UNET DSS MLevel=0
UNET DZMax Abort=0
UNET Convert EG Bridges=0
UNET Use Existing IB Tables=0
UNET Froude Limit=0
UNET Froude Power=0
Write IC File=0
Echo Input=False
Echo Output=False
Write Detailed=0

--- MileBr.f01 (steady flow) ---

Flow Title=NFF Regression Equation
Program Version=4.00
Number of Profiles=1
Profile Names=P100yr
River Rch & RM=MileBr,Main      ,2204.3
725.7961
River Rch & RM=MileBr,Main      ,223.9
754.5882
Boundary for River Rch & Prof#=MileBr,Main      ,1
Up Type=0
Dn Type=3
Dn Slope=0.028564

--- MileBr.g01 (geometry) ---

Geom Title=USGS 10m DEM
Program Version=4.00

River Reach=MileBr          ,Main
Reach XY= 30
     1789988.078      203168.645     1789947.918      203147.189
     1789874.748      203138.387     1789848.891      203145.539
     1789754.266       203151.59     1789696.928      203133.112
     1789606.945      203092.114     1789539.503       203056.17
     1789491.331      203021.708     1789369.788      203004.292
     1789186.732      202987.987      1789112.62      202971.312
       1789005.9      202924.621      1788974.58      202907.082
     1788905.389      202854.511     1788754.649       202774.74
       1788707.6      202763.429     1788672.599      202763.819
     1788622.372      202749.347     1788564.298      202708.172
     1788532.389      202675.713     1788456.469      202654.258
     1788316.732      202596.492      1788272.17      202563.483
     1788243.562      202536.526     1788189.648      202446.852
     1788170.392      202403.391      1788161.04      202319.218
     1788145.636      202269.705     1788145.812      202244.541

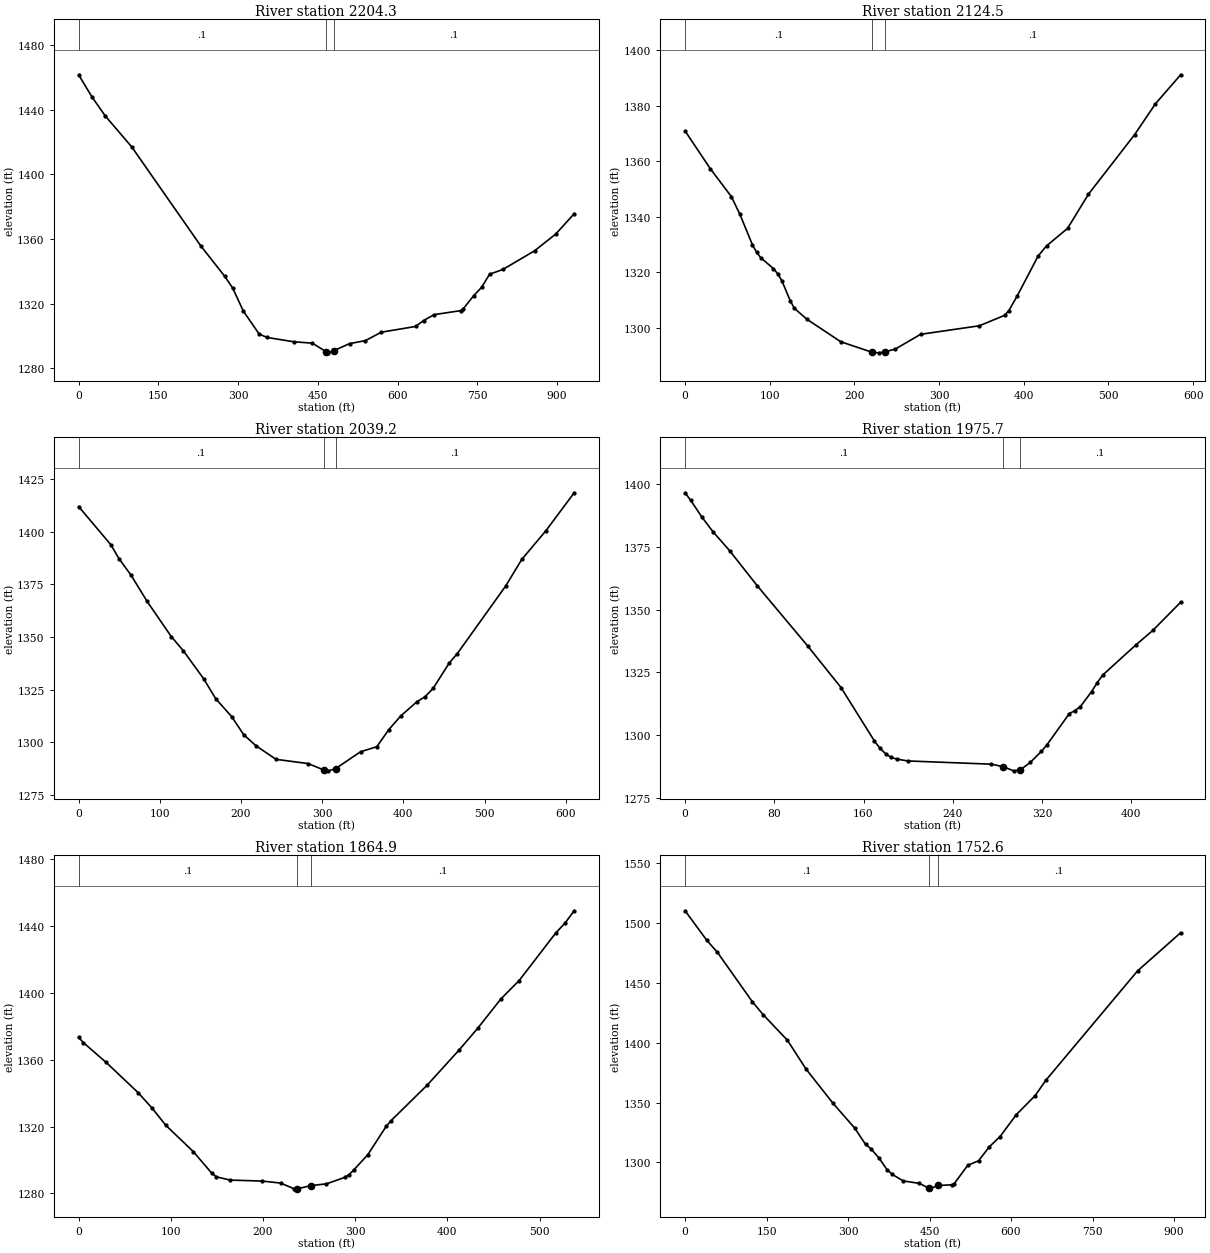
Type RM Length L Ch R = 1 ,2204.3  ,85.2,79.8,75.4
XS GIS Cut Line= 3
     1790078.353      202699.906     1789962.743      203206.338
     1790002.171       203616.96
#Sta/Elev= 30
       0 1461.52      25 1447.87      50 1436.11    99.9 1416.93   229.8 1355.72
   274.7 1336.96   289.7  1329.7   309.7 1315.48   339.6  1301.2   354.6 1299.12
   404.6 1296.47   439.5 1295.62     465 1290.42   469.5 1289.63     480 1290.97
   509.5 1295.33   539.3 1297.18   569.2 1302.38   633.8 1305.94   648.7 1309.59
   668.6 1313.24   718.3  1315.7   723.2 1316.78   743.1    1325     758 1330.16
   772.9 1338.24   797.8 1341.15   857.4 1352.68   897.2 1363.03     932 1375.61
#Mann= 3 , 0 , 0
       0      .1       0     465    .045       0     480      .1       0
Bank Sta=465,480
XS Rating Curve= 0 ,0
Exp/Cntr=0.3,0.1

Type RM Length L Ch R = 1 ,2124.5  ,82.3,85.2,88.2
XS GIS Cut Line= 3
     1789896.588      202913.039     1789897.921      203255.707
     1789873.921      203497.041
#Sta/Elev= 30
       0 1370.89    29.8 1357.32    54.6  1347.3    64.6    1341    79.5 1329.97
    84.4 1327.27    89.4  1325.3   104.3 1321.41   109.3 1319.56   114.2  1317.1
   124.2  1309.8   129.1  1307.1     144 1303.14   183.8  1295.1   220.6 1291.33
   228.4  1291.1   235.6 1291.42   248.3 1292.47   278.1 1297.76   347.6 1300.84
   377.3 1304.59   382.3 1306.28   392.2 1311.57   416.9 1325.92   426.8 1329.57
   451.6 1335.84   476.3 1348.14   530.8 1369.55   555.5  1380.7   585.2 1391.11
#Mann= 3 , 0 , 0
       0      .1       0   220.6    .045       0   235.6      .1       0
Bank Sta=220.6,235.6
XS Rating Curve= 0 ,0
Exp/Cntr=0.3,0.1

Type RM Length L Ch R = 1 ,2039.2  ,63.7,63.5,63.2
XS GIS Cut Line= 2
     1789852.587      202839.706     1789775.254      203445.041
#Sta/Elev= 30
       0 1411.86    39.7 1393.75    49.6 1387.21    64.5 1379.36    84.3 1366.92
   114.1 1350.21     129 1343.48   153.8 1330.31   168.7 1320.84   188.5 1312.23
   203.4 1303.65   218.3  1298.5   243.1 1292.01   282.8    1290   301.6 1287.01
   307.6 1286.56   316.6 1287.65   347.3 1295.62   367.2 1297.98     382  1306.1
   396.9 1312.65   416.8 1319.39   426.7 1321.72   436.6 1325.66   456.4 1337.66
   466.4 1342.17   525.9 1374.16   545.8 1386.81   575.5 1400.41   610.3 1418.39
#Mann= 3 , 0 , 0
       0      .1       0   301.6    .045       0   316.6      .1       0
Bank Sta=301.6,316.6
XS Rating Curve= 0 ,0
Exp/Cntr=0.3,0.1

Type RM Length L Ch R = 1 ,1975.7  ,105,110.9,116.7
XS GIS Cut Line= 2
     1789784.587      202859.706     1789732.587      203301.041
#Sta/Elev= 30
       0 1396.59       5  1393.6      15 1386.95      25 1381.08    39.9 1373.53
    64.9 1359.44   109.8 1335.63   139.8    1319   169.8 1297.68   174.8 1294.79
   179.8 1292.59   184.8 1291.17   189.7 1290.49   199.7 1289.74   274.6 1288.46
   285.3 1287.46   294.6  1285.8   300.3  1286.1   309.6 1289.18   319.6 1293.58
   324.6 1296.22   344.5 1308.57   349.5 1309.77   354.5 1311.39   364.5 1317.34
   369.5 1320.89   374.5 1323.96   404.4 1336.03   419.4 1341.73   444.4 1352.97
#Mann= 3 , 0 , 0
       0      .1       0   285.3    .045       0   300.3      .1       0
Bank Sta=285.3,300.3
XS Rating Curve= 0 ,0
Exp/Cntr=0.3,0.1

Type RM Length L Ch R = 1 ,1864.9  ,109.6,112.2,114.9
XS GIS Cut Line= 2
     1789736.587      202883.706     1789539.253      203383.708
#Sta/Elev= 30
       0 1373.26       5 1370.16    29.9 1358.25    64.7 1340.13    79.6 1331.02
    94.6 1320.71   124.4 1304.99   144.3  1292.2   149.3 1289.99   164.2 1288.01
   199.1 1287.42     219 1286.23   233.9 1282.78   237.3 1282.84   252.3 1284.73
   268.8 1285.76   288.7 1289.63   293.6 1291.34   298.6 1294.18   313.6  1303.1
   333.5 1320.01   338.4 1323.23   378.3 1344.84   413.1 1365.94     433 1378.76
   457.9  1396.1   477.8 1407.15   517.6 1435.61   527.6  1441.5   537.5 1448.82
#Mann= 3 , 0 , 0
       0      .1       0   237.3    .045       0   252.3      .1       0
Bank Sta=237.3,252.3
XS Rating Curve= 0 ,0
Exp/Cntr=0.3,0.1

Type RM Length L Ch R = 1 ,1752.6  ,383.4,381.7,379.9
XS GIS Cut Line= 3
     1789763.278      202657.367     1789500.586      203146.373
     1789344.118      203467.342
#Sta/Elev= 30
       0 1510.11    39.6 1485.66    59.5  1475.4   123.9 1434.11   143.7 1423.35
   188.3 1402.03     223 1377.72   272.6 1349.21   312.2 1328.66   332.1 1315.08
     342 1311.48   356.8 1303.68   371.7 1294.01   381.6 1289.96   401.4 1284.53
   431.2 1282.51   449.7 1278.22     451 1277.93   464.7 1280.72   490.7 1281.28
   495.6 1282.38   520.4 1297.61   540.2 1301.33   560.1 1313.07   579.9 1321.63
   609.6 1339.83   644.4 1355.78   664.2 1368.65   832.8 1459.86   912.2 1491.77
#Mann= 3 , 0 , 0
       0      .1       0   449.7    .045       0   464.7      .1       0
Bank Sta=449.7,464.7
XS Rating Curve= 0 ,0
Exp/Cntr=0.3,0.1

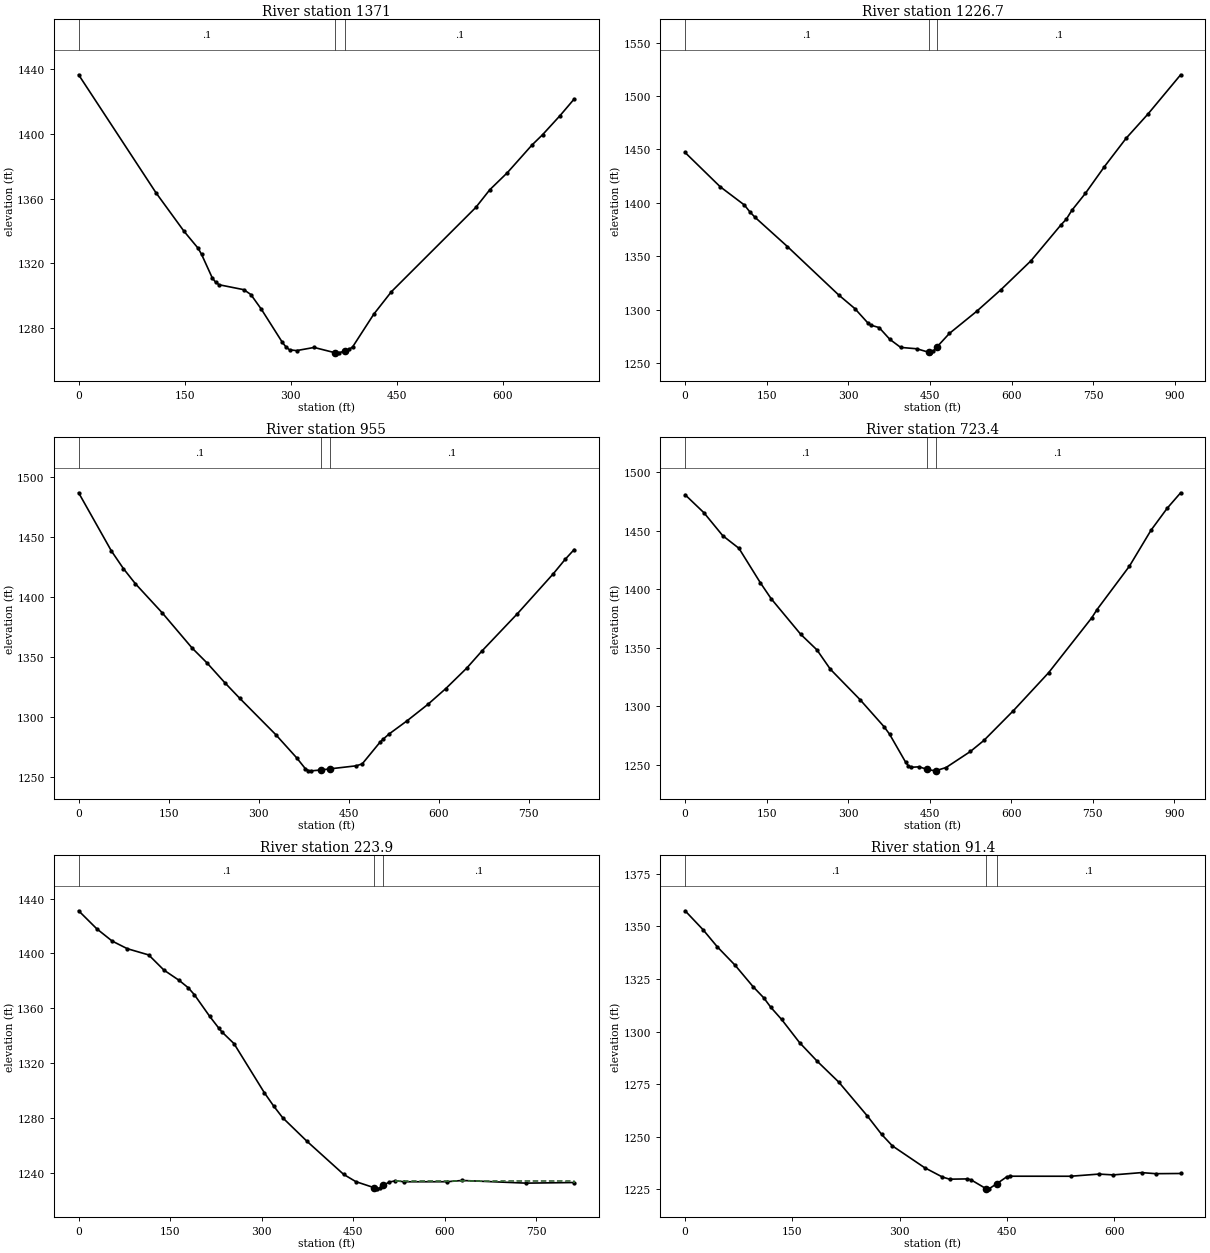
Type RM Length L Ch R = 1 ,1371    ,144.5,144.2,144.7
XS GIS Cut Line= 2
     1789329.919      202649.038     1789044.585      203289.041
#Sta/Elev= 30
       0 1436.59   109.3 1363.74   149.1 1339.86     169 1329.39   173.9 1325.58
   188.8 1311.27   193.8 1308.35   198.8 1306.85   233.6 1303.81   243.5 1300.83
   258.4 1291.73   288.2 1271.19   293.2 1268.44   298.2 1266.68   308.1 1266.18
     333 1268.13     362 1264.92   367.8  1264.8     377 1266.02   382.7 1266.94
   387.6 1268.58   417.4 1288.72   442.3 1302.59   561.6 1354.63   581.4 1365.57
   606.3 1376.14   641.1 1393.22     656 1399.56   680.8  1411.4   700.7 1421.62
#Mann= 3 , 0 , 0
       0      .1       0     362    .045       0     377      .1       0
Bank Sta=362,377
XS Rating Curve= 0 ,0
Exp/Cntr=0.3,0.1

Type RM Length L Ch R = 1 ,1226.7  ,271.2,271.7,271.5
XS GIS Cut Line= 3
      1789225.21      202524.936     1789042.896      202942.204
     1788847.618      203353.098
#Sta/Elev= 30
       0 1447.04    64.3 1415.04   108.9 1397.87   118.8 1391.52   128.7 1386.24
   188.1  1358.9   282.1 1313.64   311.8 1300.88   336.6 1286.92   341.5 1285.29
   356.4 1283.09   376.2 1272.01     396 1264.51   425.7 1263.21   447.9 1259.91
   450.4 1259.42   455.4 1260.81   462.9 1265.08   485.4 1277.54   535.4 1298.22
   580.3 1318.61   635.3 1345.61   690.3 1379.16   700.3 1384.59   710.3 1392.77
   735.3 1408.76   770.3  1433.8   810.3 1460.45   850.3 1483.07   910.3 1519.82
#Mann= 3 , 0 , 0
       0      .1       0   447.9    .045       0   462.9      .1       0
Bank Sta=447.9,462.9
XS Rating Curve= 0 ,0
Exp/Cntr=0.3,0.1

Type RM Length L Ch R = 1 ,955     ,233.8,231.6,231.4
XS GIS Cut Line= 2
     1788983.844      202430.445     1788635.398      203179.485
#Sta/Elev= 30
       0 1487.03    54.7 1438.37    74.6 1423.73    94.6 1411.07   139.4 1386.72
   189.1 1357.38     214 1344.92   243.8 1328.33   268.7 1315.29   328.5 1285.07
   363.3 1265.74   378.2 1256.42   383.2 1254.94   388.2 1254.76   404.8 1255.51
   419.8 1256.47   462.8 1258.96   472.8  1260.6   502.6 1278.78   507.6  1281.2
   517.6 1285.56   547.4 1296.51   582.3 1310.31   612.1 1323.48     647 1340.58
   671.8 1354.58   731.6  1386.1   791.3 1419.39   811.2 1431.49   826.1 1439.61
#Mann= 3 , 0 , 0
       0      .1       0   404.8    .045       0   419.8      .1       0
Bank Sta=404.8,419.8
XS Rating Curve= 0 ,0
Exp/Cntr=0.3,0.1

Type RM Length L Ch R = 1 ,723.4   ,483.5,499.5,514.7
XS GIS Cut Line= 3
     1788750.392      202306.189      1788594.13      202733.696
     1788401.013      203146.941
#Sta/Elev= 30
       0 1480.66    34.6  1465.3    69.3 1445.65      99 1434.91   138.5  1405.4
   158.3 1391.82   212.7  1361.4   242.4 1348.16   267.2 1331.57   321.6 1305.69
   366.1 1282.39     376 1276.12   405.7 1252.09   410.6 1249.14   415.6 1247.86
   430.4 1248.24   445.7 1245.96   460.1 1244.81   460.7 1244.84     480 1247.66
   524.6 1261.33   549.4 1270.74   603.9 1296.28   668.4 1328.58   747.7 1375.44
   757.6 1382.62   817.1 1419.64   856.8 1450.33   886.5 1469.08   911.3 1482.33
#Mann= 3 , 0 , 0
       0      .1       0   445.7    .045       0   460.7      .1       0
Bank Sta=445.7,460.7
XS Rating Curve= 0 ,0
Exp/Cntr=0.3,0.1

Type RM Length L Ch R = 1 ,223.9   ,133.2,132.5,127.1
XS GIS Cut Line= 4
     1788622.866      202214.745      1788190.15      202463.261
     1787911.093      202594.833     1787907.589      202597.324
#Sta/Elev= 30
       0 1431.06    29.9 1417.85    54.9 1408.98    79.8  1403.4   114.8 1398.86
   139.7 1387.82   164.7  1380.3   179.6 1374.91   189.6 1369.86   214.6 1354.14
   229.5 1345.53   234.5 1342.82   254.5  1334.2   304.4 1298.27   319.4 1288.74
   334.3 1280.12   374.2 1262.91   434.1 1238.84   454.1 1233.54     484 1229.13
     489 1228.28     494  1229.1     499 1230.83     509 1233.24   518.9 1234.13
   533.8 1233.43   603.5 1233.46   628.4 1234.39   732.9 1232.44   811.8 1232.89
#Mann= 3 , 0 , 0
       0      .1       0     484    .045       0     499      .1       0
#XS Ineff= 2 , 0
                             519         1234.12
Permanent Ineff=
       F       F
Bank Sta=484,499
XS Rating Curve= 0 ,0
Exp/Cntr=0.3,0.1

Type RM Length L Ch R = 1 ,91.4    ,55.4,56.4,60.8
XS GIS Cut Line= 3
     1788534.458      202121.714     1788147.733      202341.586
     1787974.642      202519.355
#Sta/Elev= 30
       0 1357.35      25  1348.4      45 1340.25      70 1331.46      95 1321.33
     110 1316.01     120 1311.45     135 1305.73     160 1294.76   184.9 1285.84
   214.9 1275.98   254.9 1259.88   274.9 1251.12   289.9 1245.68   334.9 1235.34
   359.9 1230.88   369.9 1229.87   394.9    1230   399.9 1229.55   421.2 1225.29
   424.9 1225.28   436.2 1227.78   449.8 1230.99   454.8 1231.28   539.1 1231.26
   578.8 1232.29   598.7  1231.9   638.4 1232.99   658.2 1232.48     693 1232.57
#Mann= 3 , 0 , 0
       0      .1       0   421.2    .045       0   436.2      .1       0
Bank Sta=421.2,436.2
XS Rating Curve= 0 ,0
Exp/Cntr=0.3,0.1

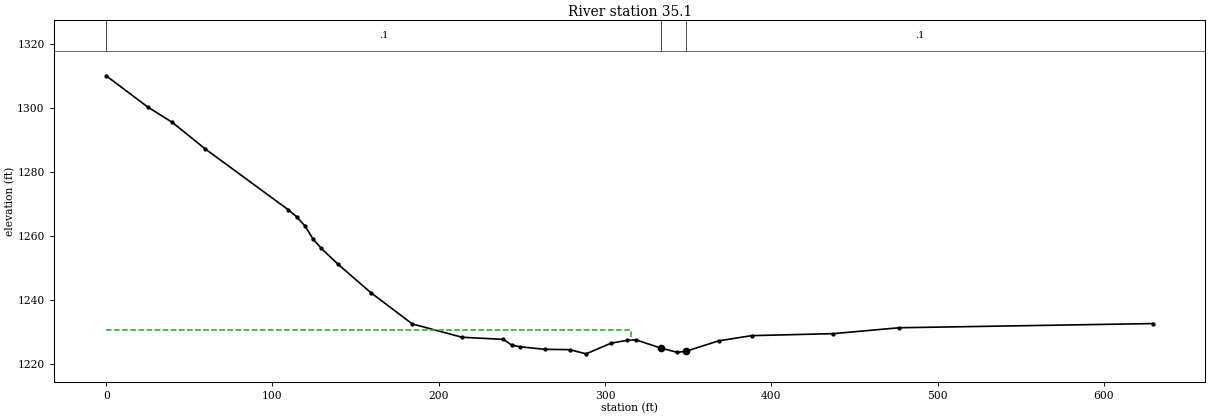
Type RM Length L Ch R = 1 ,35.1    ,23.4,35.1,46.7
XS GIS Cut Line= 3
     1788447.133      202113.917     1788111.867      202299.483
     1787959.048      202492.845
#Sta/Elev= 30
       0  1310.1    24.9 1300.37    39.8  1295.5    59.7 1287.17   109.5 1268.19
   114.5 1266.02   119.4 1263.21   124.4 1259.05   129.4 1256.08   139.3  1251.2
   159.2 1242.23   184.1 1232.46     214  1228.3   238.9 1227.63   243.8 1225.88
   248.8 1225.32   263.8 1224.52   278.7 1224.42   288.6 1223.11   303.6 1226.44
   313.5 1227.35   318.5  1227.5   333.7 1224.89   343.4 1223.59   348.7 1223.92
   368.3 1227.17   388.1  1228.8   437.4 1229.43   476.8 1231.27   629.6 1232.58
#Mann= 3 , 0 , 0
       0      .1       0   333.7    .045       0   348.7      .1       0
#XS Ineff= 2 , 0
          315.59 1230.69
Permanent Ineff=
       F       F
Bank Sta=333.7,348.7
XS Rating Curve= 0 ,0
Exp/Cntr=0.3,0.1

Chan Stop Cuts=-1
Use User Specified Reach Order=0